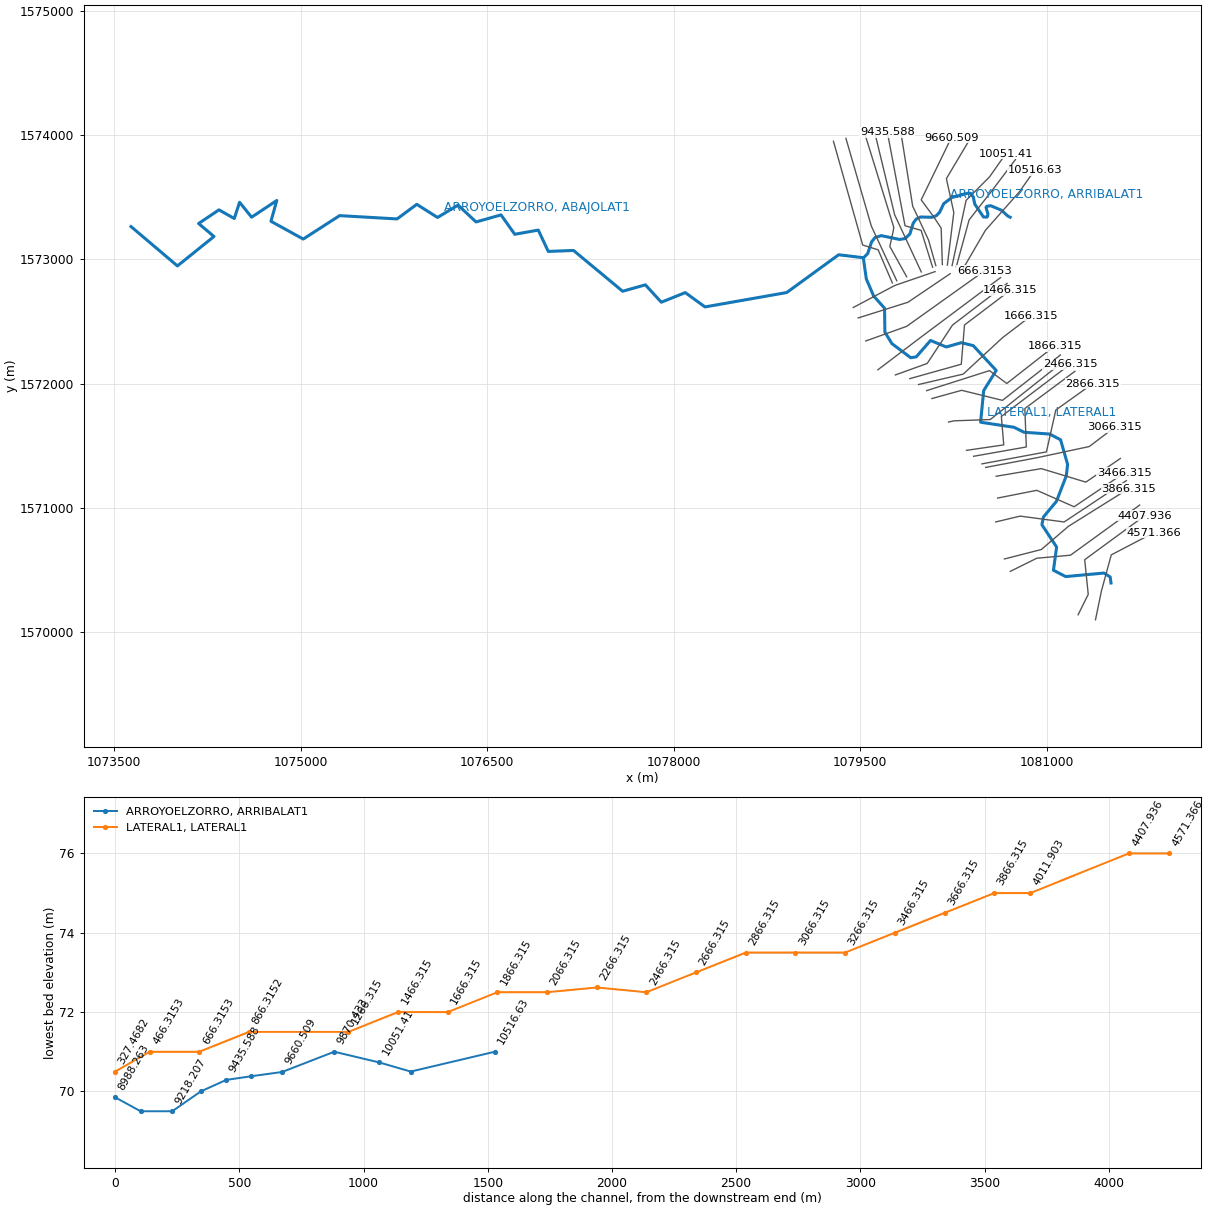
--- HECRAS_v1.prj (project) ---

Proj Title=HECRAS_v1
Current Geom=g01
Default Exp/Contr=0.3,0.1
SI Units
Geom File=g01
Y Axis Title=Elevation
X Axis Title(PF)=Main Channel Distance
X Axis Title(XS)=Station
BEGIN DESCRIPTION:
END DESCRIPTION:
DSS Export Rating Curves= 0
DSS Export Rating Curve Sorted= 0
DSS Export Volume Flow Curves= 0
DXF OffsetX= 0
DXF OffsetY= 0
DXF ScaleX= 1
DXF ScaleY= 10

--- HECRAS_v1.g01 (geometry) ---

Geom Title=HECRAS_v1
Program Version=5.01

Junct Name=1
Junct Desc=, 0 , 0 ,-1 ,0
Up River,Reach=ARROYOELZORRO   ,ARRIBALAT1
Dn River,Reach=ARROYOELZORRO   ,ABAJOLAT1
Junc L&A=0,0

River Reach=ARROYOELZORRO   ,ARRIBALAT1
Reach XY= 30
    1080707.4374    1573339.5833    1080687.7523    1573349.7434
    1080636.3172     1573396.416    1080550.5921    1573432.2935
    1080519.1595     1573427.531    1080513.4445     1573418.641
    1080528.0495    1573365.6184    1080525.5095    1573345.6159
     1080519.477    1573340.2184    1080492.1719    1573342.1234
    1080422.9568    1573444.6761     1080410.836    1573501.8389
    1080390.1985    1573530.9431    1080370.0901    1573533.8535
    1080237.7982    1573498.1347    1080173.2397    1573449.1867
     1080139.536     1573378.935    1080113.4599    1573351.9355
    1080078.0847    1573339.3843    1079986.1122    1573341.3699
    1079950.6469    1573323.7062    1079927.6034    1573291.4759
    1079900.9914    1573205.3105    1079862.9313    1573168.1895
     1079817.723    1573160.9037    1079670.7934    1573191.5554
     1079620.597    1573176.3569    1079592.4691    1573141.0177
    1079561.4908    1573047.1475    1079528.5191    1573013.8644

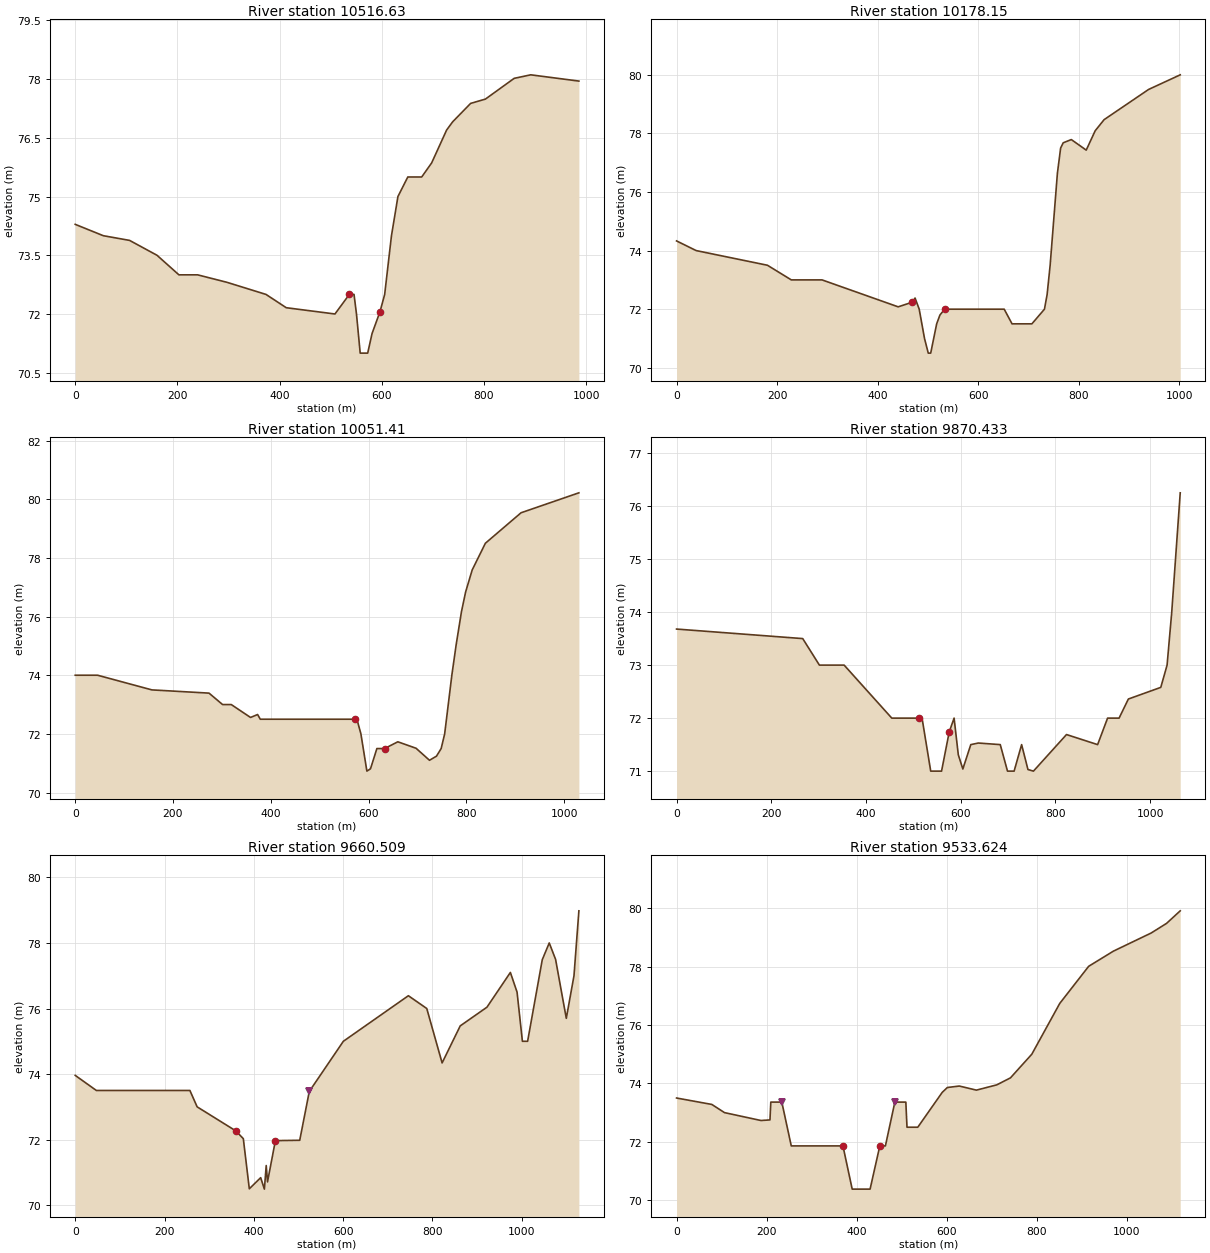
Type RM Length L Ch R = 1 ,10516.63,326.71,338.48,272.19
XS GIS Cut Line= 4
    1080327.0311    1572922.9204    1080508.3292    1573234.2431
    1080782.3396     1573544.788    1080904.0514    1573717.6348
#Sta/Elev= 30
       0   74.29   54.96      74  106.41   73.88  160.09    73.5  202.95      73
  239.59      73  296.77   72.81  373.39    72.5  413.09   72.16  508.37      72
  536.55    72.5  545.68    72.5   550.5      72  557.78      71  572.44      71
  580.98    71.5  596.55   72.06  605.68    72.5  618.98      74  631.62      75
  650.95    75.5  678.17    75.5  697.65   75.86  726.96    76.7  738.77   76.91
  773.94   77.38  802.87   77.49  859.15   78.02   891.6   78.11  985.81   77.95
#Mann= 0 , 0 , 0
Bank Sta=536.55,596.55
XS Rating Curve= 0 ,0
Exp/Cntr=0.3,0.1

Type RM Length L Ch R = 1 ,10178.15,130.71,126.74,122.71
XS GIS Cut Line= 4
    1080274.1143    1572941.9705    1080377.2263    1573318.1105
    1080566.5631    1573560.6676    1080749.9587    1573803.7037
#Sta/Elev= 30
       0   74.33   39.05      74  180.78    73.5  228.31      73  289.46      73
  440.96   72.08  469.28   72.24  474.55   72.38  482.82      72  493.37      71
  500.83    70.5  505.67    70.5  517.56    71.5  524.04    71.8  533.39      72
  651.94      72  667.53    71.5  707.05    71.5  732.02      72  737.33    72.5
  743.35    73.5  757.79   76.64  764.21    77.5  769.34   77.68  785.48   77.79
  815.14   77.43  832.97   78.09  850.74   78.47  939.19    79.5 1002.19      80
#Mann= 0 , 0 , 0
Bank Sta=469.28,533.39
XS Rating Curve= 0 ,0
Exp/Cntr=0.3,0.1

Type RM Length L Ch R = 1 ,10051.41,150.51,180.98,211.46
XS GIS Cut Line= 4
    1080240.2476    1572950.4372    1080352.9475    1573475.0008
     1080541.224    1573663.8071    1080671.8044    1573849.7252
#Sta/Elev= 30
       0      74   45.82      74  156.83    73.5  273.69   73.39  301.48      73
  319.19      73  358.67   72.56  373.11   72.66  378.61    72.5  572.77    72.5
  576.26    72.5  584.43      72  596.67   70.73  604.06   70.81  617.13    71.5
  632.85    71.5  659.99   71.73  697.24   71.51  724.75    71.1  739.02   71.24
  748.62    71.5  755.78      72  770.45      74  779.39   75.05  790.06   76.16
  798.65   76.84  812.08   77.59  839.05    78.5  912.04   79.54 1030.36   80.22
#Mann= 0 , 0 , 0
Bank Sta=572.77,632.85
XS Rating Curve= 0 ,0
Exp/Cntr=0.3,0.1

Type RM Length L Ch R = 1 ,9870.433,205.56,209.92,222.26
XS GIS Cut Line= 4
    1080202.1475    1572954.6705    1080254.1813     1573378.091
    1080194.4311    1573650.0588     1080377.746    1573958.0837
#Sta/Elev= 30
       0   73.68  266.43    73.5  301.61      73  353.82      73  454.44      72
  512.51      72  518.34      72  536.65      71  559.54      71  575.74   71.74
  586.02      72  594.87   71.31  604.48   71.04  621.28    71.5  637.17   71.53
   683.5    71.5  698.79      71  712.74      71  728.62    71.5  741.99   71.03
  753.58      71  823.39   71.69  889.07    71.5  910.13      72   934.4      72
  953.99   72.36 1022.46   72.58 1035.75      73 1045.59      74 1063.51   76.25
#Mann= 0 , 0 , 0
Bank Sta=512.51,575.74
XS Rating Curve= 0 ,0
Exp/Cntr=0.3,0.1

Type RM Length L Ch R = 1 ,9660.509,133.24,126.88,116.59
XS GIS Cut Line= 5
    1080161.9306    1572958.9446    1080152.5873    1573251.4818
    1080095.9811    1573338.1023    1079991.8435    1573479.1967
    1080234.5059    1573980.1218
#Sta/Elev= 30
       0   73.96   47.29    73.5  256.84    73.5  273.09      73  359.35   72.27
  376.51   72.03  389.93    70.5  415.39   70.84   423.7   70.49  427.79   71.21
  430.69   70.71  448.34   71.97  502.86   71.98  524.29   73.47  600.56      75
  746.21   76.39  787.41      76  821.77   74.34  862.37   75.47  922.19   76.04
  974.68    77.1  989.65    76.5 1001.61      75 1013.29      75 1046.13   77.49
 1061.74      78 1075.93    77.5 1099.93    75.7 1117.14      77 1128.13   78.98
#Mann= 0 , 0 , 0
Levee=0,,,-1,524.29,73.47035,,	339
Bank Sta=359.35,448.34
XS Rating Curve= 0 ,0
Exp/Cntr=0.3,0.1

Type RM Length L Ch R = 1 ,9533.624,62.94,98.04,133.14
XS GIS Cut Line= 5
    1080109.3166     1572950.726    1080050.9978    1573155.8972
     1079943.577     1573386.726    1079923.5675    1573427.4895
    1079827.7994    1574025.7831
#Sta/Elev= 30
       0    73.5   78.34   73.28   106.5      73  187.46   72.73  207.56   72.75
  209.43   73.36  233.88   73.36  254.88   71.86  369.71   71.86  390.29   70.38
  430.04   70.38  451.65   71.86  464.08   71.86  485.08   73.36  509.48   73.36
  512.06    72.5  536.06    72.5  590.18   73.69  601.72   73.86  628.31   73.91
   666.3   73.77  711.47   73.95  741.98   74.19  789.41      75  851.53   76.74
  915.75   78.01  970.82   78.53 1054.62   79.15 1088.83   79.48 1119.22   79.91
#Mann= 0 , 0 , 0
Levee=-1,233.88,73.36314,-1,485.08,73.36273,	340,	339
Bank Sta=369.71,451.65
XS Rating Curve= 0 ,0
Exp/Cntr=0.3,0.1

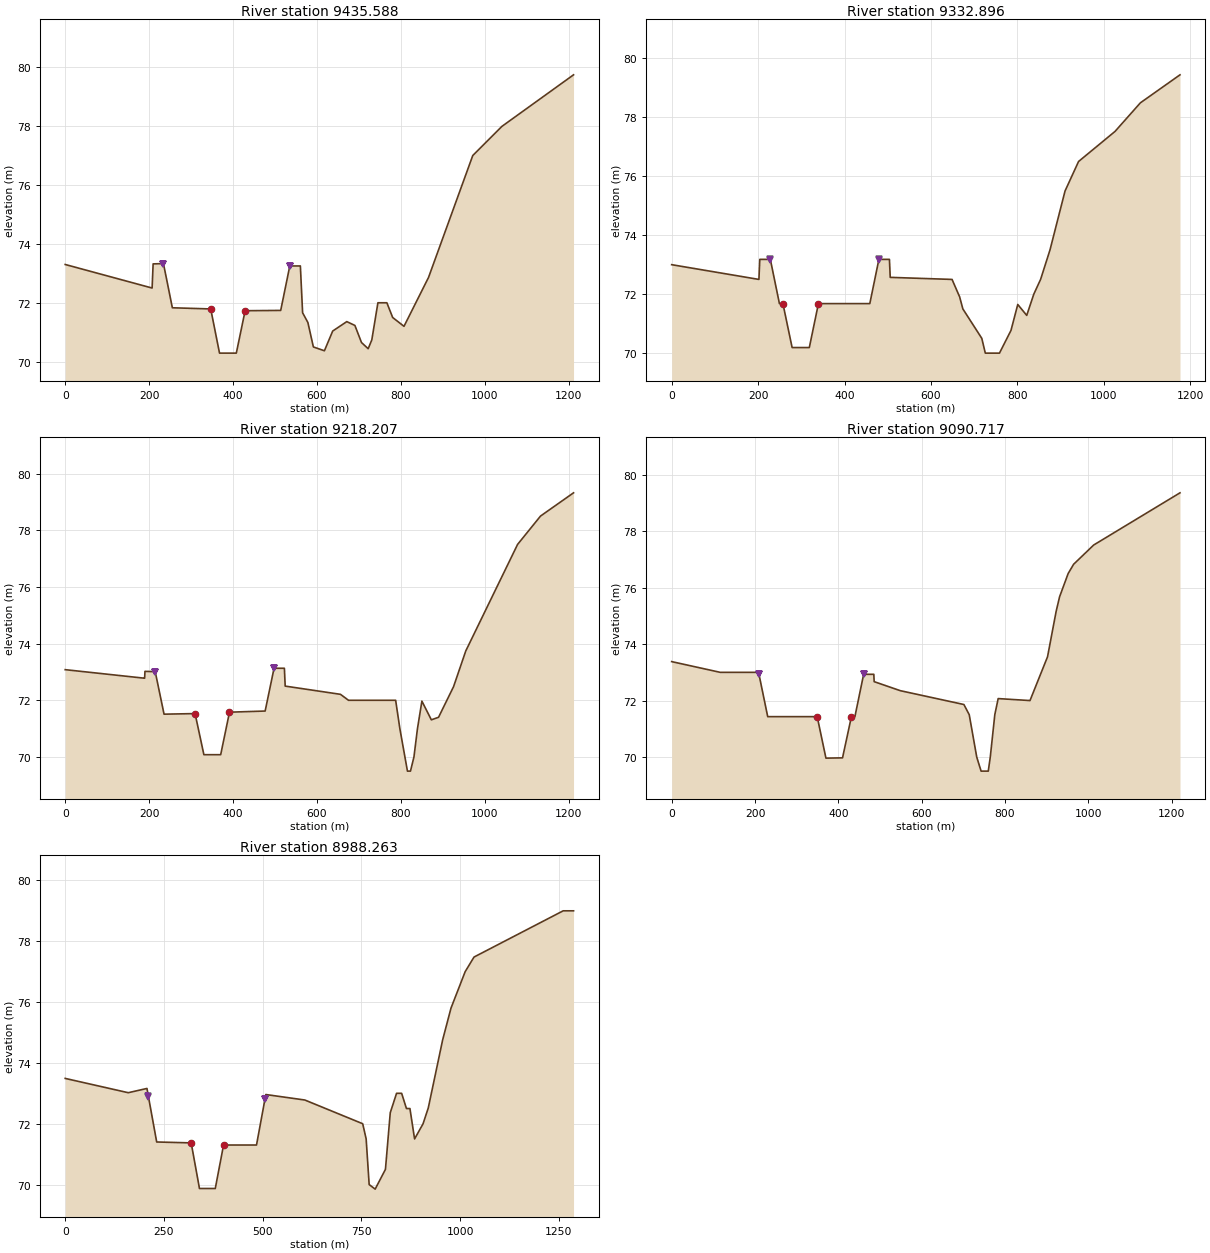
Type RM Length L Ch R = 1 ,9435.588,137.8,102.69,67.58
XS GIS Cut Line= 4
    1080083.4932    1572937.8142    1079991.2064    1573234.1482
     1079861.851     1573271.218    1079719.4258    1574024.0897
#Sta/Elev= 30
       0    73.3  207.07    72.5  209.48   73.32   234.1   73.33  255.29   71.83
   346.7   71.79   367.7   70.29   407.7   70.29   428.7   71.73  513.46   71.74
  535.12   73.25   560.3   73.25  565.65   71.66  578.22   71.33   591.3    70.5
   617.6   70.37  637.36   71.04  670.92   71.36  690.23   71.23  705.96   70.65
  721.87   70.44  730.54   70.74  745.07      72   766.4      72  780.24    71.5
  807.22    71.2  865.68   72.86  971.08      77 1040.58   77.99 1211.16   79.74
#Mann= 0 , 0 , 0
Levee=-1,234.1,73.32671,-1,535.13,73.24612,	340,	339
Bank Sta=346.7,428.7
XS Rating Curve= 0 ,0
Exp/Cntr=0.3,0.1

Type RM Length L Ch R = 1 ,9332.896,141.46,114.69,87.92
XS GIS Cut Line= 3
    1079992.4764    1572899.5025    1079778.3077     1573359.714
    1079621.0007    1574009.6964
#Sta/Elev= 30
       0      73  201.91    72.5  203.94   73.18  228.34   73.18  249.34   71.68
  257.43   71.68  278.72   70.19  318.56   70.19  339.62   71.68  458.54   71.68
  479.54   73.18  503.94   73.18  505.77   72.57  648.86    72.5  666.35   71.91
  673.85    71.5  717.72    70.5  725.81      70  758.58      70   785.2   70.77
  800.92   71.65  821.67   71.28  838.01      72  853.74    72.5  875.49    73.5
  910.34    75.5  941.61    76.5 1025.97   77.52 1084.68   78.49 1176.35   79.44
#Mann= 0 , 0 , 0
Levee=-1,228.34,73.17561,-1,479.54,73.17561,	340,	339
Bank Sta=257.43,339.62
XS Rating Curve= 0 ,0
Exp/Cntr=0.3,0.1

Type RM Length L Ch R = 1 ,9218.207,100.72,127.49,154.26
XS GIS Cut Line= 5
    1079875.0012    1572860.7674    1079739.5342    1573104.6079
    1079763.8079    1573214.4359    1079771.7076    1573257.0082
    1079542.2605    1573998.6897
#Sta/Elev= 30
       0   73.08  188.03   72.78  189.26   72.78  189.98   73.02  214.44   73.01
   235.5   71.51  309.42   71.53  330.42   70.08  370.42   70.08  391.42   71.58
  476.37   71.62  497.57   73.13  522.19   73.13  524.11    72.5  655.81   72.21
  674.96      72  787.28      72  797.42   70.99  815.41    69.5   822.6    69.5
  830.87      70  839.26      71  849.81   71.97  872.36   71.31  889.48    71.4
  925.24   72.48  954.33   73.74 1077.82    77.5 1132.44    78.5 1211.08   79.32
#Mann= 0 , 0 , 0
Levee=-1,214.44,73.01493,-1,497.56,73.12814,	340,	339
Bank Sta=309.42,391.42
XS Rating Curve= 0 ,0
Exp/Cntr=0.3,0.1

Type RM Length L Ch R = 1 ,9090.717,68.21,102.45,136.69
XS GIS Cut Line= 3
    1079795.4143     1572828.594    1079590.7473    1573268.3881
    1079386.4735    1573974.1363
#Sta/Elev= 30
       0   73.38  116.52      73  206.87      73  208.66   72.99  230.48   71.43
  349.22   71.43  370.18   69.96  410.01   69.97  431.31   71.43  439.68   71.43
  460.68   72.93  485.08   72.93   485.9   72.67  548.67   72.35  701.25   71.86
  714.03    71.5  732.03      70  742.52    69.5  759.73    69.5  764.57      70
  775.42    71.5  783.49   72.07  859.84      72  901.93   73.55  922.59   75.16
  930.92   75.68   951.4    76.5  964.59   76.83 1012.64   77.51  1219.8   79.36
#Mann= 0 , 0 , 0
Levee=-1,209.48,72.93304,-1,460.68,72.93301,	340,	339
Bank Sta=349.22,431.31
XS Rating Curve= 0 ,0
Exp/Cntr=0.3,0.1

Type RM Length L Ch R = 1 ,8988.263,137.11,103.08,68.73
XS GIS Cut Line= 4
    1079759.8543     1572810.814     1079645.554    1573077.6204
    1079521.3471    1573116.0751    1079286.2491    1573950.7471
#Sta/Elev= 30
       0   73.49  159.73   73.02  207.05   73.16  231.71    71.4  319.07   71.37
  340.07   69.87  380.07   69.87  401.07    71.3  484.52    71.3  508.09   72.96
  606.87   72.78   753.5      72  762.21    71.5  769.83      70  785.04   69.85
  811.06    70.5  823.24   72.36   839.2      73   852.1      73  864.25    72.5
   873.1    72.5  884.88    71.5  906.35      72  919.57   72.52     956   74.76
  977.07    75.8 1012.99      77  1035.4   77.48 1261.22      79 1287.43      79
#Mann= 0 , 0 , 0
Levee=-1,210.7,72.89437,-1,505.8,72.80102,	340,	339
Bank Sta=319.07,401.07
XS Rating Curve= 0 ,0
Exp/Cntr=0.3,0.1

River Reach=LATERAL1        ,LATERAL1
Reach XY= 30
    1081518.2289    1570397.8927    1081511.8789    1570446.5761
    1081461.9254    1570477.9029    1081153.9498    1570449.5395
    1081055.5246    1570500.3396    1081080.9247    1570687.0299
    1080962.8144    1570866.1003    1080974.8794    1570928.9654
    1081079.6547    1571054.6957    1081159.0298    1571260.4361
    1081169.1898    1571352.5113    1081112.6747    1571549.9967
    1081025.0445    1571595.7168    1080818.6691    1571610.3218
     1080738.024    1571650.3269    1080469.4184    1571690.9669
     1080494.501     1571945.285    1080595.1487    1572107.2103
    1080410.6808    1572306.9182    1080314.1606    1572330.7307
    1080193.5104    1572296.1232    1080067.1451    1572348.5108
    1079951.8924     1572216.748    1079907.7598     1572209.763
    1079755.9945    1572323.4282    1079699.7969    1572415.5034
    1079697.2569    1572607.9088    1079609.6267    1572706.0165
    1079550.5716    1572842.8593    1079526.3885    1573012.8008

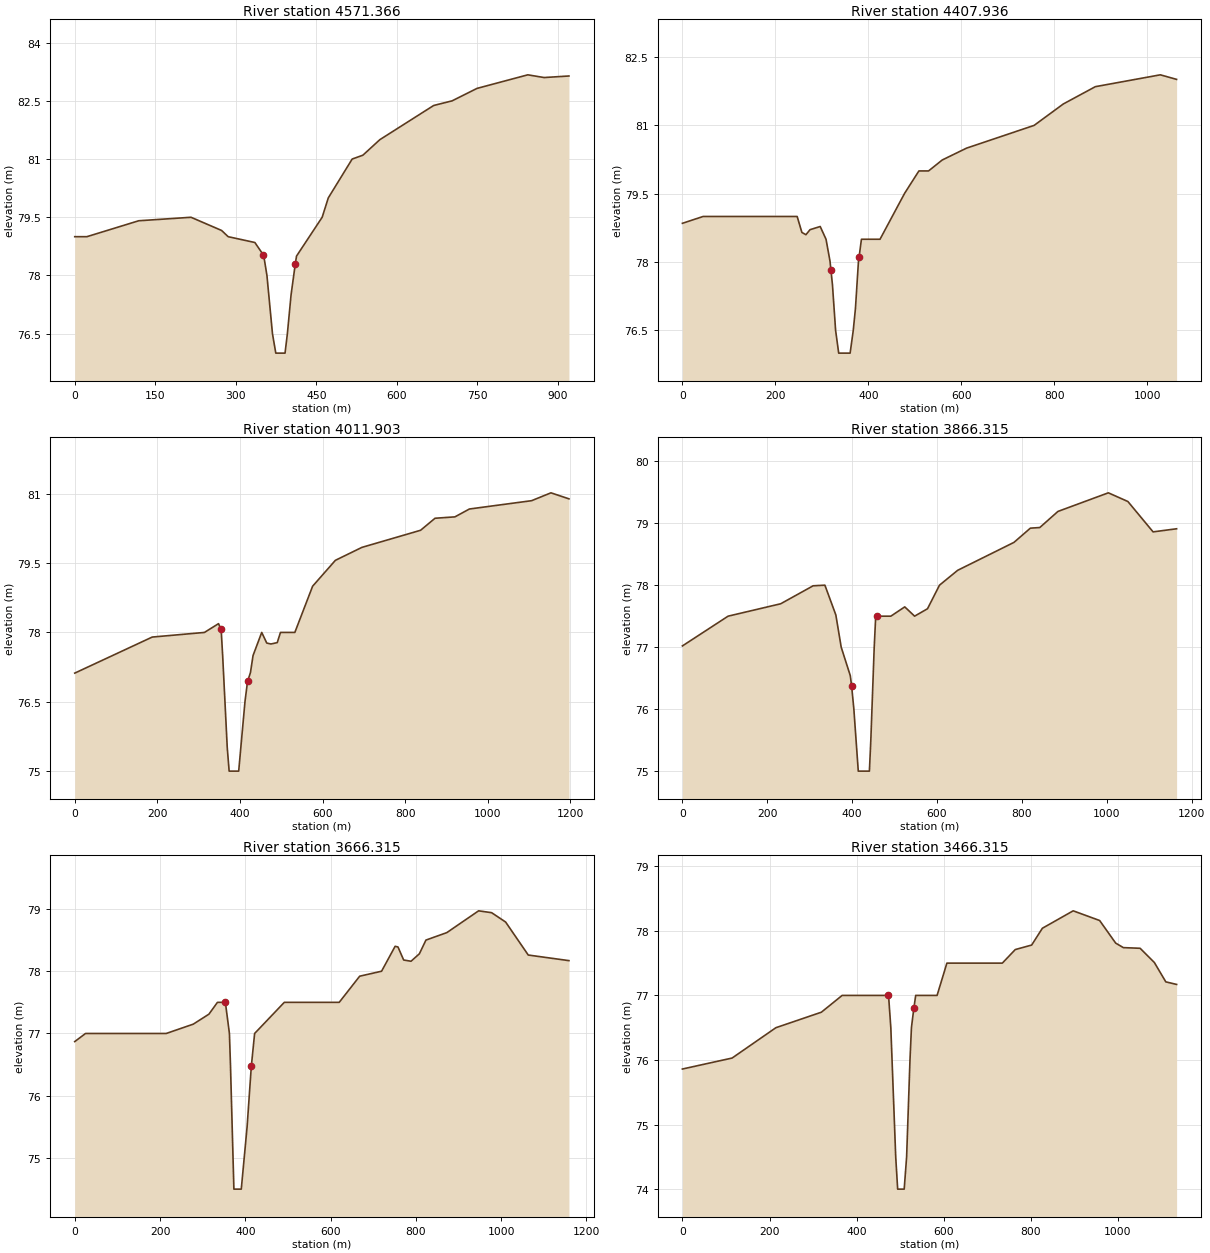
Type RM Length L Ch R = 1 ,4571.366,152.41,163.43,174.48
XS GIS Cut Line= 4
    1081393.6367    1570101.9591     1081441.199    1570332.9487
    1081520.5742    1570623.9909    1081860.0449    1570801.3279
#Sta/Elev= 28
       0      79   22.59      79  119.12   79.41  216.56    79.5  273.55   79.16
  285.76      79  335.51   78.85  350.79   78.54  352.15    78.5  357.99      78
   368.3    76.5  374.48      76   391.7      76  396.05    76.5  402.91    77.5
   410.8    78.3  413.09    78.5  460.85    79.5   472.3      80  516.74      81
  536.76    81.1  568.37    81.5  668.54   82.38  703.02    82.5  749.23   82.82
  843.89   83.17   874.3    83.1  920.51   83.14
#Mann= 0 , 0 , 0
Bank Sta=350.79,410.8
XS Rating Curve= 0 ,0
Exp/Cntr=0.3,0.1

Type RM Length L Ch R = 1 ,4407.936,443.54,396.03,348.49
XS GIS Cut Line= 4
    1081253.6858     1570142.195    1081335.3655    1570306.4903
    1081306.8387     1570585.175    1081790.6318    1570939.9528
#Sta/Elev= 30
       0   78.85   44.52      79  246.94      79  257.12   78.65  265.78    78.6
  274.62   78.71  296.55   78.78  309.08    78.5  317.63   78.02  319.66   77.82
  322.92    77.5  329.69    76.5  336.34      76  360.94      76  367.68    76.5
  372.39   76.98  378.77      78  380.37   78.12  385.27    78.5  425.28    78.5
   478.3   79.51  508.98      80  529.77      80  559.12   80.24   611.4    80.5
  756.96      81  819.72   81.47  888.71   81.85 1028.57   82.11 1063.56   82.01
#Mann= 0 , 0 , 0
Bank Sta=319.66,380.37
XS Rating Curve= 0 ,0
Exp/Cntr=0.3,0.1

Type RM Length L Ch R = 1 ,4011.903,127.44,145.59,163.74
XS GIS Cut Line= 4
    1080708.7383    1570491.5304    1080921.5307    1570597.1121
    1081192.4902    1570621.3451    1081748.8517    1571024.5408
#Sta/Elev= 30
       0   77.12  187.64    77.9  314.07      78  348.21   78.19  353.85   78.07
  354.92      78  358.17    77.5  369.27   75.51   373.9      75     397      75
  412.29   76.51  418.41   76.94  425.44   77.13  431.74    77.5  452.77      78
  464.98   77.77  475.06   77.75  490.37   77.78  498.14      78  532.95      78
     576      79  631.16   79.56  695.41   79.84  837.48   80.21  872.46   80.47
  920.67    80.5  955.68   80.67 1106.34   80.85 1153.18   81.02 1196.69   80.89
#Mann= 0 , 0 , 0
Bank Sta=353.85,418.41
XS Rating Curve= 0 ,0
Exp/Cntr=0.3,0.1

Type RM Length L Ch R = 1 ,3866.315,225.37,200,174.75
XS GIS Cut Line= 4
    1080660.7755    1570590.9984    1080958.4221    1570667.3234
    1081175.4436    1570853.3408    1081659.8275    1571156.3035
#Sta/Elev= 30
       0   77.02  107.61    77.5  231.58    77.7  308.02   77.99  335.73      78
  361.51   77.52  374.15      77  395.57   76.54  398.75   76.37  403.98      76
  414.38      75  440.59      75  443.95    75.5  451.88   76.99  455.46    77.5
  458.75    77.5  491.12    77.5  523.92   77.65  547.09    77.5  577.54   77.62
  605.73      78   648.6   78.24  781.16   78.69  819.93   78.92  842.05   78.93
  884.91   79.19  1003.6   79.49 1049.65   79.35 1109.03   78.86 1164.44   78.91
#Mann= 0 , 0 , 0
Bank Sta=398.75,458.75
XS Rating Curve= 0 ,0
Exp/Cntr=0.3,0.1

Type RM Length L Ch R = 1 ,3666.315,208.53,200,191.35
XS GIS Cut Line= 4
    1080591.5109    1570888.9546    1080787.6296    1570935.8453
     1081141.525    1570888.6593    1081641.6243    1571220.7033
#Sta/Elev= 30
       0   76.87   25.29      77  214.53      77  278.02   77.15  314.66   77.31
  334.66    77.5  353.25    77.5  362.73      77  365.18    76.5  373.23    74.5
  390.54    74.5  404.18    75.5  414.05   76.47  421.85      77  491.43    77.5
  620.24    77.5  668.23   77.92  719.59      78  751.34    78.4  758.02   78.39
  771.36   78.18  788.64   78.16  808.24   78.28   823.6    78.5  872.58   78.62
  947.16   78.97  977.67   78.94 1010.47   78.79 1063.58   78.26 1158.97   78.17
#Mann= 0 , 0 , 0
Bank Sta=353.25,414.05
XS Rating Curve= 0 ,0
Exp/Cntr=0.3,0.1

Type RM Length L Ch R = 1 ,3466.315,196.37,200,203.63
XS GIS Cut Line= 4
     1080606.752    1571080.9971    1080921.7505    1571143.2625
    1081221.8512    1571010.8655    1081624.2068    1571282.5043
#Sta/Elev= 30
       0   75.86   114.1   76.03  214.64    76.5  319.04   76.74  366.74      77
  471.31      77  473.26      77  478.48    76.5   489.7    74.5  494.18      74
  509.17      74  514.75    74.5  522.46      76  525.79    76.5  531.31    76.8
  535.57      77  584.65      77  607.19    77.5  734.46    77.5  764.18   77.71
  801.81   77.78  826.41   78.04  897.13   78.31  957.89   78.16  994.72   77.81
  1012.4   77.74 1050.79   77.73 1083.48   77.51 1109.79   77.21 1134.57   77.17
#Mann= 0 , 0 , 0
Bank Sta=471.31,531.31
XS Rating Curve= 0 ,0
Exp/Cntr=0.3,0.1

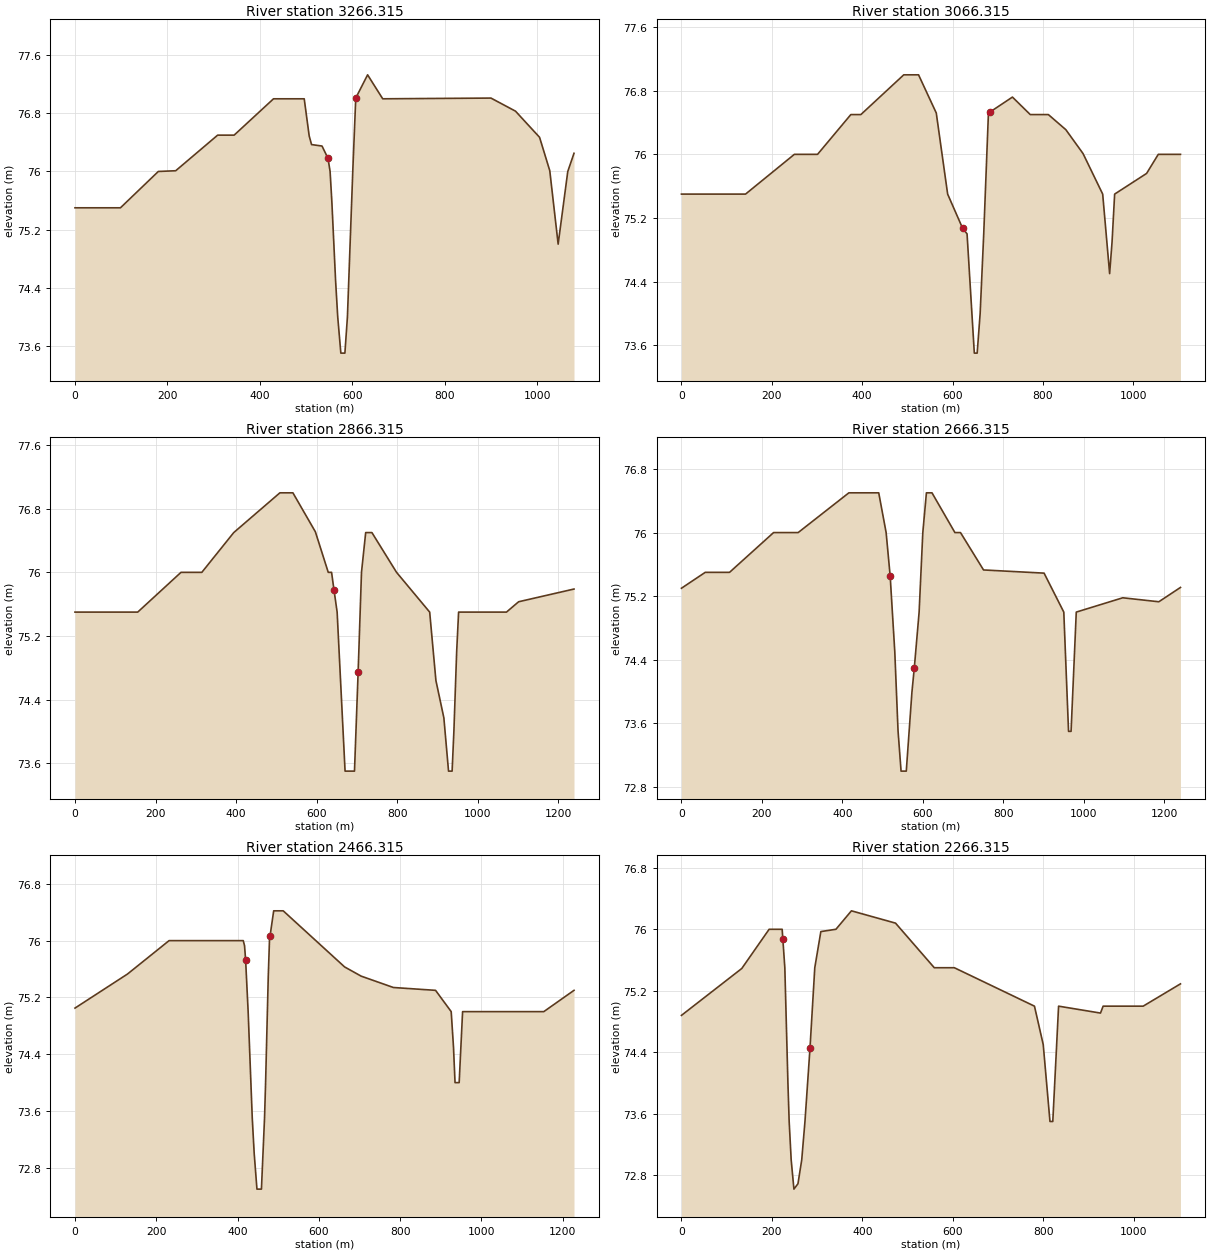
Type RM Length L Ch R = 1 ,3266.315,184.79,200,215.21
XS GIS Cut Line= 4
    1080595.0101    1571256.4086    1080957.9986    1571317.8097
    1081316.1518    1571209.0849    1081593.8293    1571399.4434
#Sta/Elev= 30
       0    75.5   98.33    75.5  180.22      76  217.81   76.01  308.54    76.5
  344.18    76.5  429.31      77  495.72      77  506.44   76.49  511.56   76.37
  534.21   76.35  547.17   76.18  551.66      76  555.49   75.58  563.52    74.5
  568.16      74  574.91    73.5  583.66    73.5  589.15      74  600.69      76
  607.17   77.01  632.77   77.33  665.46      77  899.52   77.01   952.6   76.83
 1004.65   76.47 1026.74   76.01 1044.84      75 1065.64      76  1079.1   76.25
#Mann= 0 , 0 , 0
Bank Sta=547.17,607.17
XS Rating Curve= 0 ,0
Exp/Cntr=0.3,0.1

Type RM Length L Ch R = 1 ,3066.315,165.67,200,234.33
XS GIS Cut Line= 4
    1080510.4142    1571327.4268    1080932.1897    1571407.2786
    1081343.4433    1571495.4044    1081546.3129    1571648.9608
#Sta/Elev= 30
       0    75.5  141.84    75.5  249.87      76  301.21      76  374.81    76.5
     397    76.5  491.95      77  524.68      77   563.9   76.52  589.07    75.5
  622.19   75.07  632.03      75   648.1    73.5  654.41    73.5  661.02      74
  668.93      75   679.2    76.5  682.19   76.53  732.44   76.72  771.91    76.5
  811.96    76.5  850.64   76.31  888.68   76.01  932.18    75.5  947.53    74.5
  952.92    74.9  958.64    75.5 1029.37   75.76 1055.21      76 1104.29      76
#Mann= 0 , 0 , 0
Bank Sta=622.19,682.19
XS Rating Curve= 0 ,0
Exp/Cntr=0.3,0.1

Type RM Length L Ch R = 1 ,2866.315,192.19,200,207.81
XS GIS Cut Line= 4
    1080480.4185    1571356.0345    1080998.9119    1571452.4209
    1081074.7051    1571789.2748    1081372.5527    1572002.1389
#Sta/Elev= 30
       0    75.5  155.77    75.5  263.17      76  314.87      76  394.08    76.5
  508.65      77  540.95      77  596.73   76.51   628.7      76  636.94      76
  642.91   75.78  650.75    75.5  670.45    73.5  693.83    73.5  702.91   74.75
  711.22      76  721.63    76.5  737.08    76.5  798.23      76   880.5    75.5
  895.95   74.64   915.7   74.17   927.3    73.5  936.17    73.5  940.58      74
  947.45      75  952.29    75.5 1071.15    75.5 1101.27   75.63 1238.74   75.79
#Mann= 0 , 0 , 0
Bank Sta=642.91,702.91
XS Rating Curve= 0 ,0
Exp/Cntr=0.3,0.1

Type RM Length L Ch R = 1 ,2666.315,198.69,200,201.31
XS GIS Cut Line= 4
    1080413.8089    1571417.1216    1080837.3071    1571491.9031
     1080825.417    1571801.0496    1081227.9039    1572100.2957
#Sta/Elev= 30
       0    75.3   59.16    75.5   119.6    75.5  229.11      76  290.18      76
  416.36    76.5  490.59    76.5  509.01      76   519.1   75.45  530.54    74.5
  538.59   73.51  546.13      73  559.12      73  573.11   73.99   579.1    74.3
  591.04      75  600.21      76  609.19    76.5  623.05    76.5  680.09      76
  693.95      76  751.24   75.53  901.81   75.49  950.83      75  962.64    73.5
  968.92    73.5  981.86      75 1097.49   75.18 1187.19   75.13 1240.97   75.31
#Mann= 0 , 0 , 0
Bank Sta=519.1,579.1
XS Rating Curve= 0 ,0
Exp/Cntr=0.3,0.1

Type RM Length L Ch R = 1 ,2466.315,249.51,200,150.31
XS GIS Cut Line= 4
    1080356.2232    1571464.6942    1080655.8705    1571508.8005
    1080636.4999    1571737.3738    1081190.6132    1572157.6623
#Sta/Elev= 29
       0   75.05  129.25   75.53  231.45      76  414.03      76  417.14   75.93
  419.77   75.73  426.04      75  436.16    73.5  440.94      73  447.68    72.5
   458.7    72.5  466.35    73.5  468.97      74  475.54    75.5  478.49      76
  479.78   76.06  488.87   76.42   512.3   76.42  663.32   75.63  704.07    75.5
  783.39   75.34  887.13    75.3   925.6      75  931.26    74.5  935.05      74
   945.2      74  953.65      75 1153.43      75 1227.74    75.3
#Mann= 0 , 0 , 0
Bank Sta=419.77,479.78
XS Rating Curve= 0 ,0
Exp/Cntr=0.3,0.1

Type RM Length L Ch R = 1 ,2266.315,208.24,200,191.76
XS GIS Cut Line= 4
    1080212.2983    1571692.6391    1080255.2301    1571702.1731
    1080547.5626    1571712.6135     1081148.028    1572190.0326
#Sta/Elev= 30
       0   74.88  133.44   75.49  193.89      76  222.74      76  224.25   75.87
  228.63    75.5  235.47      74  238.21    73.5  242.68      73  248.74   72.62
  257.67   72.69     266      73  273.15    73.5  284.25   74.45  294.88    75.5
  308.28   75.97  341.67      76  375.91   76.24  473.47   76.08  559.14    75.5
  603.46    75.5  780.73      75  800.12    74.5  815.02    73.5  821.27    73.5
  834.08      75  926.78   74.91  932.61      75 1021.16      75 1103.63   75.29
#Mann= 0 , 0 , 0
Bank Sta=224.25,284.25
XS Rating Curve= 0 ,0
Exp/Cntr=0.3,0.1

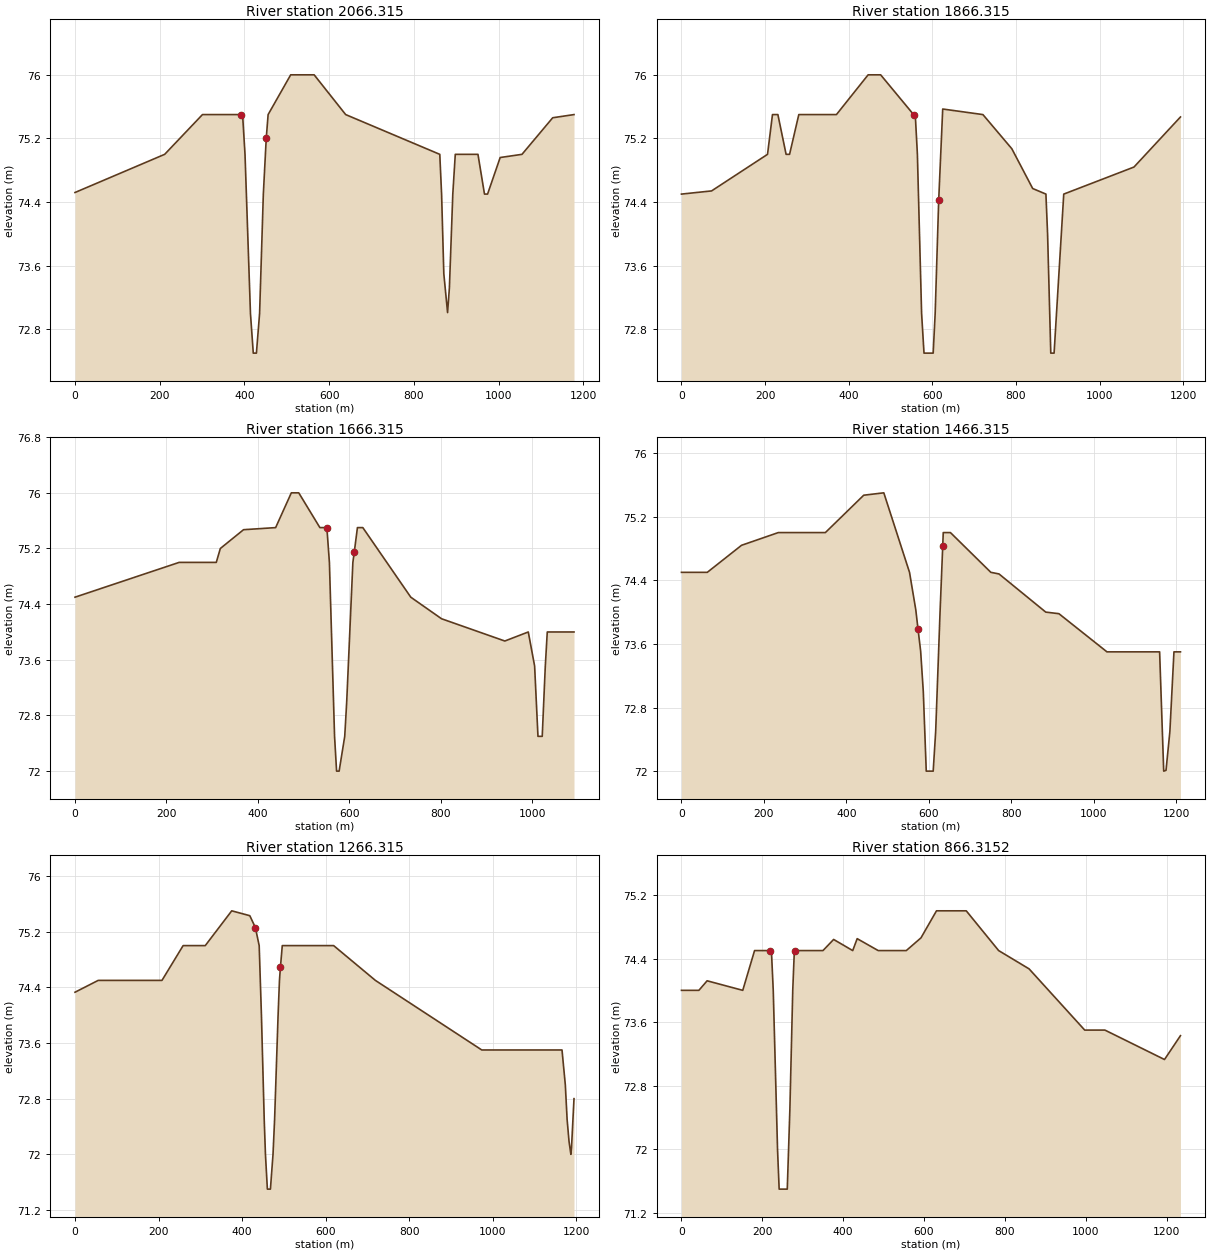
Type RM Length L Ch R = 1 ,2066.315,211.93,200,188.07
XS GIS Cut Line= 4
    1080078.1307    1571881.4182    1080317.4153     1571947.621
    1080645.3778    1571866.6952    1081111.3766    1572231.5927
#Sta/Elev= 30
       0   74.52   211.7      75  300.93    75.5  391.45    75.5  395.62    75.5
  401.35      75   414.2      73  420.87    72.5  428.26    72.5  435.78      73
  444.61    74.5  451.45    75.2   455.9    75.5   509.2      76  564.57      76
  638.95    75.5  861.11      75  865.39    74.5  870.63    73.5  879.49   73.01
   883.8   73.32  891.84    74.5   897.7      75  951.24      75  966.65    74.5
  973.92    74.5 1003.67   74.96 1055.17      75 1127.66   75.46 1177.94    75.5
#Mann= 0 , 0 , 0
Bank Sta=391.45,451.45
XS Rating Curve= 0 ,0
Exp/Cntr=0.3,0.1

Type RM Length L Ch R = 1 ,1866.315,158.12,200,241.88
XS GIS Cut Line= 4
    1080035.6115    1571945.0255    1080541.2594    1572105.8958
    1080680.2679    1572002.6317    1081065.8008    1572304.3412
#Sta/Elev= 30
       0    74.5   72.07   74.54  205.82      75  217.69    75.5   230.6    75.5
  250.24      75  258.55      75  280.63    75.5  370.62    75.5  446.42      76
  476.36      76  555.16    75.5  559.14    75.5  564.22      75  574.28      73
  580.04    72.5  601.97    72.5  606.75      73  615.16   74.42  624.78   75.57
  720.93    75.5  790.11   75.07  839.99   74.57  871.58    74.5  875.56      74
  883.22    72.5  891.13    72.5  914.23    74.5 1082.12   74.84 1193.34   75.47
#Mann= 0 , 0 , 0
Bank Sta=555.16,615.16
XS Rating Curve= 0 ,0
Exp/Cntr=0.3,0.1

Type RM Length L Ch R = 1 ,1666.315,177.66,200,222.34
XS GIS Cut Line= 4
    1079970.6561    1571994.2082    1080329.7154    1572077.9904
    1080643.9976    1572369.1636    1080877.7629    1572548.1553
#Sta/Elev= 30
       0    74.5  227.76      75  309.06      75  317.96    75.2   368.7   75.47
  438.91    75.5  473.27      76  489.48      76  535.71    75.5  550.97    75.5
  556.53      75   567.8    72.5  572.23      72  577.77      72  590.06    72.5
   594.4      73  607.86      75  610.97   75.15  617.83    75.5  629.63    75.5
  734.54    74.5  801.84   74.19  940.24   73.87  991.57      74 1005.43   73.51
 1012.74    72.5 1022.07    72.5 1028.71    73.5  1033.1      74 1091.56      74
#Mann= 0 , 0 , 0
Bank Sta=550.97,610.97
XS Rating Curve= 0 ,0
Exp/Cntr=0.3,0.1

Type RM Length L Ch R = 1 ,1466.315,215.04,200,184.95
XS GIS Cut Line= 4
    1079900.4549     1572041.573    1080314.2202    1572157.3594
    1080340.1248     1572473.396    1080710.0367    1572753.1583
#Sta/Elev= 30
       0    74.5   62.68    74.5  145.72   74.84   234.9      75  349.11      75
  442.19   75.47   490.9    75.5  553.27    74.5  568.45   74.03  573.79   73.79
  580.24   73.51  586.69      73  593.86      72  610.69      72  616.73    72.5
  627.34      74  633.83   74.83  635.08      75  652.52      75  750.56    74.5
  770.29   74.48  883.71      74  915.67   73.98 1032.25    73.5 1159.98    73.5
  1169.9      72 1175.51   72.01 1184.89    72.5 1194.77    73.5 1210.55    73.5
#Mann= 0 , 0 , 0
Bank Sta=573.79,633.83
XS Rating Curve= 0 ,0
Exp/Cntr=0.3,0.1

Type RM Length L Ch R = 1 ,1266.315,410.51,400,389.53
XS GIS Cut Line= 4
    1079784.3397     1572071.356    1080040.1108    1572163.4889
    1080243.6466    1572472.3018    1080683.0551    1572807.7735
#Sta/Elev= 30
       0   74.33   55.54    74.5   208.2    74.5  258.86      75  311.83      75
  375.22    75.5  418.48   75.43   431.8   75.26  440.92      75  446.31      74
  453.08   72.48  455.92      72  460.55    71.5  467.82    71.5  474.04      72
  477.82    72.5  486.19      74  489.47    74.5   491.8   74.69  496.21      75
   619.2      75  719.12    74.5  973.75    73.5 1165.84    73.5 1173.76      73
 1178.08    72.5 1182.58   72.19 1187.11      72 1188.63    72.1 1194.54    72.8
#Mann= 0 , 0 , 0
Bank Sta=431.8,491.8
XS Rating Curve= 0 ,0
Exp/Cntr=0.3,0.1

Type RM Length L Ch R = 1 ,866.3152,209.16,200,190.8
XS GIS Cut Line= 3
    1079643.4541    1572112.7012    1080005.4348    1572386.9289
    1080630.2867    1572854.0753
#Sta/Elev= 30
       0      74   43.11      74   63.48   74.12  151.63      74  180.83    74.5
  219.59    74.5  222.51    74.5  227.04      74  237.66      72  241.66    71.5
  261.73    71.5  268.17    72.5  275.29      74  279.23    74.5     280    74.5
  350.02    74.5  376.43   74.64  423.64    74.5  434.65   74.65  486.71    74.5
  556.13    74.5  592.45   74.66  630.84      75  704.45      75  784.57    74.5
   859.9   74.27  997.48    73.5 1047.47    73.5 1194.83   73.13  1234.3   73.43
#Mann= 0 , 0 , 0
Bank Sta=219.59,280
XS Rating Curve= 0 ,0
Exp/Cntr=0.3,0.1

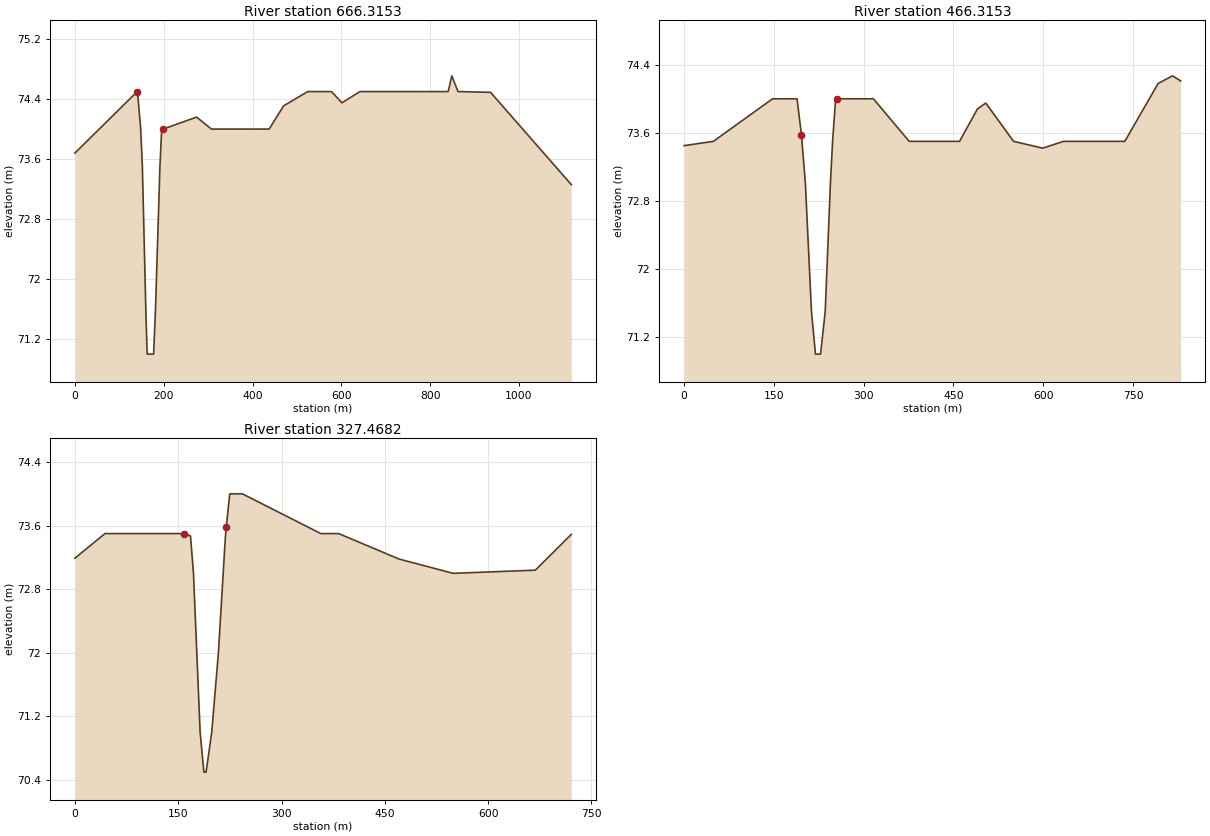
Type RM Length L Ch R = 1 ,666.3153,201.09,200,198.91
XS GIS Cut Line= 3
     1079545.912    1572344.5175     1079874.612    1572461.9099
    1080500.4923    1572908.3154
#Sta/Elev= 25
       0   73.68  138.79   74.49  141.01    74.5  148.02   74.02  151.99    73.5
  160.17    71.5  162.81      71  177.32      71  181.77   71.63  191.54    73.5
  195.51      74  198.79      74  273.97   74.16  307.56      74   437.4      74
  470.25   74.31  524.23    74.5   577.9    74.5  601.32   74.35   641.8    74.5
  840.62    74.5  848.79   74.71  862.69    74.5  935.95   74.49  1117.8   73.26
#Mann= 0 , 0 , 0
Bank Sta=138.79,198.79
XS Rating Curve= 0 ,0
Exp/Cntr=0.3,0.1

Type RM Length L Ch R = 1 ,466.3153,133.35,138.85,144.35
XS GIS Cut Line= 3
    1079485.0302    1572529.6118     1079885.609      1572655.92
    1080224.8188    1572885.3892
#Sta/Elev= 26
       0   73.45   48.82    73.5  147.69      74  188.66      74  195.95   73.58
  202.63      73  212.77    71.5  219.46      71  227.92      71  235.69    71.5
  244.38      73  248.04    73.5  253.15      74  255.95      74  316.28      74
  376.01    73.5  460.25    73.5     490   73.88  504.04   73.95  550.53    73.5
  599.18   73.42  633.96    73.5  736.37    73.5  792.01   74.18  816.14   74.27
  829.56   74.21
#Mann= 0 , 0 , 0
Bank Sta=195.95,255.95
XS Rating Curve= 0 ,0
Exp/Cntr=0.3,0.1

Type RM Length L Ch R = 1 ,327.4682,124.13,327.54,124.31
XS GIS Cut Line= 3
    1079445.6949    1572613.6877    1079779.4184    1572790.7109
    1080103.7223    1572902.2829
#Sta/Elev= 20
       0   73.19   43.77    73.5  158.42    73.5  167.88   73.47   172.2      73
  181.88      71  187.32    70.5  190.49    70.5  198.68      71   208.4      72
  218.41   73.44   219.8   73.58  224.86      74  243.24      74  357.09    73.5
     383    73.5  470.57   73.18  549.23      73  668.55   73.04  720.73   73.49
#Mann= 0 , 0 , 0
Bank Sta=158.42,219.8
XS Rating Curve= 0 ,0
Exp/Cntr=0.3,0.1

River Reach=ARROYOELZORRO   ,ABAJOLAT1
Reach XY= 30
    1079528.5191    1573013.8644    1079327.7203    1573037.6709
    1078910.1353    1572733.9715    1078253.1058    1572618.3051
    1078094.2524    1572733.3828     1077901.525    1572656.1992
    1077773.5463    1572795.8368    1077590.4555    1572744.3908
    1077195.6486    1573072.3463    1076992.2968    1573064.6889
    1076912.2578    1573236.1591    1076722.9953    1573202.6476
    1076612.4146    1573358.3916    1076411.5354    1573301.7432
     1076266.837    1573437.2883    1076101.9001    1573337.8544
    1075934.8719    1573443.2967    1075776.3981    1573325.9612
    1075314.2113    1573352.5123    1075021.8357    1573164.1616
    1074762.1036    1573307.0204    1074809.0672    1573474.3696
     1074606.396     1573339.961    1074509.6906    1573460.0821
    1074467.1477    1573329.4493    1074343.8516    1573398.9026
    1074180.2065    1573289.1003    1074303.8995    1573184.8543
    1074009.9468    1572948.0517    1073636.6961    1573264.4416