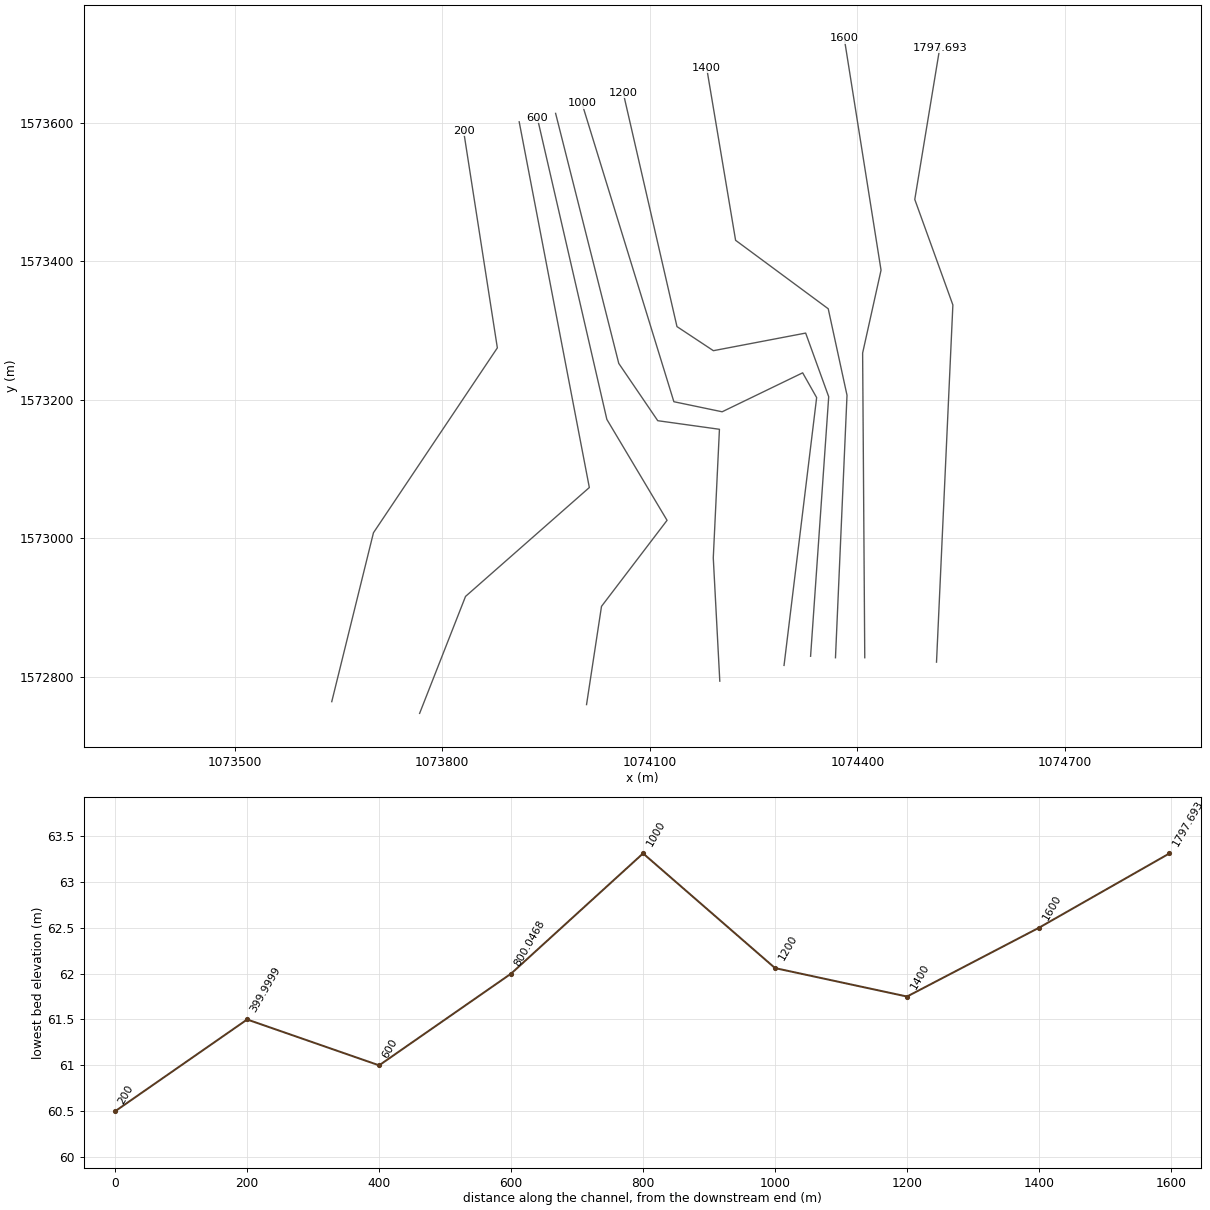
HEC-RAS study HECRAS_v1.prj: HECRAS_v1

--- HECRAS_v1.g01 (geometry) --- (continued)

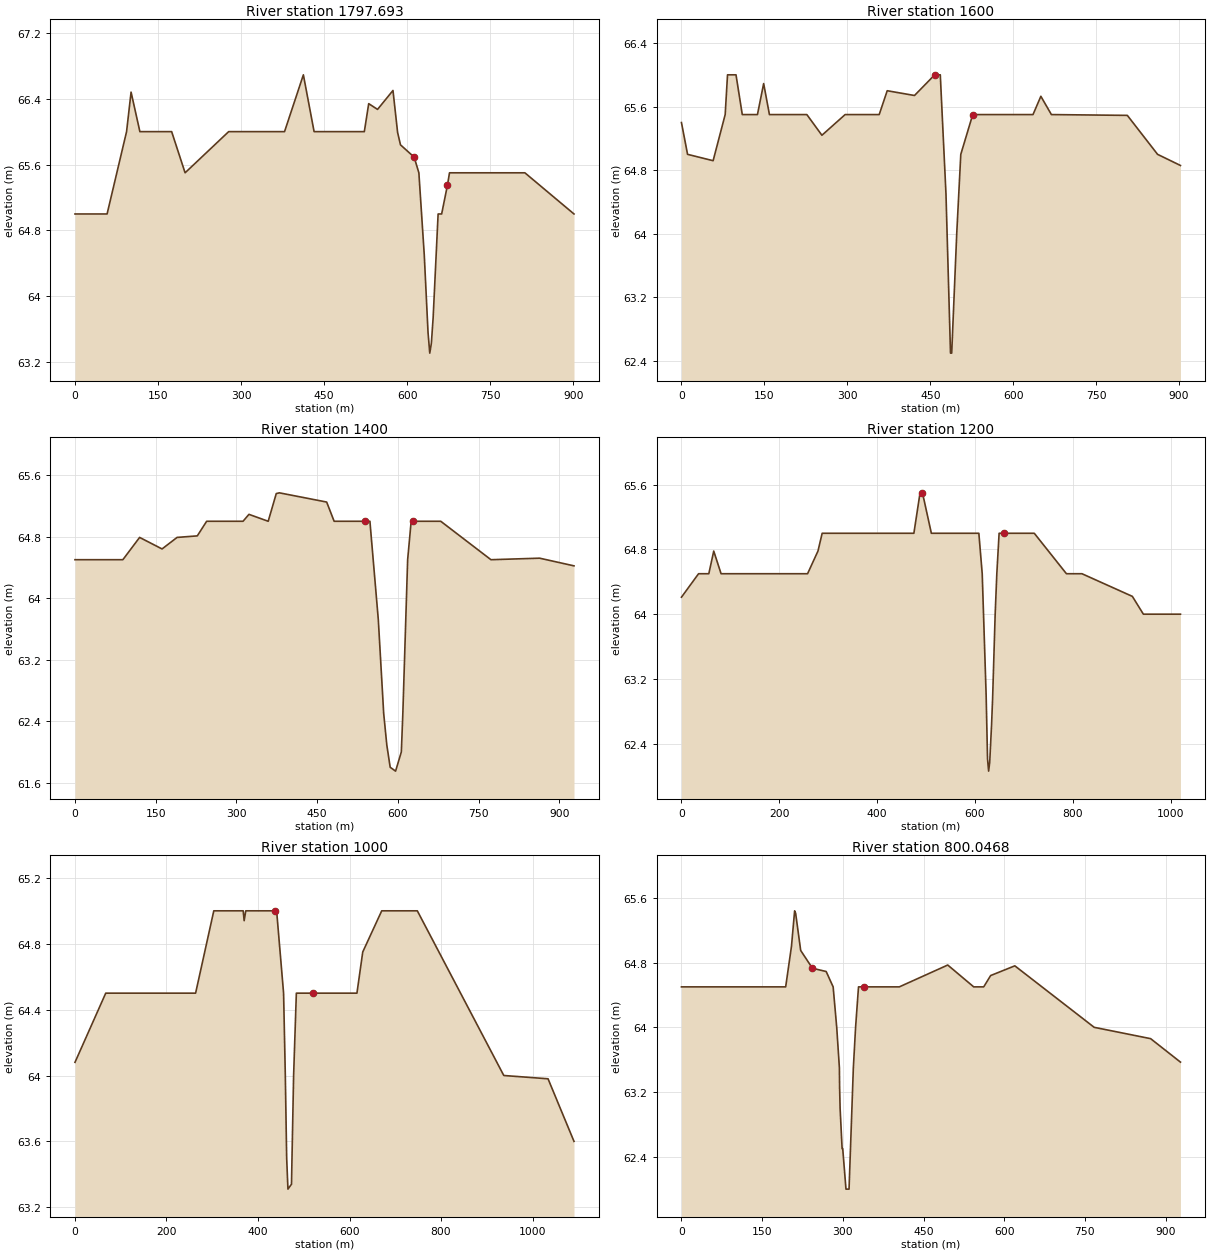
Type RM Length L Ch R = 1 ,1797.693,214.45,197.69,185.65
XS GIS Cut Line= 4
    1074514.5018    1572820.8495    1074538.1554    1573337.1533
    1074483.0853    1573489.6785    1074519.2643    1573709.0575
#Sta/Elev= 30
       0      65   57.98      65   93.17      66  101.31   66.48  117.22      66
   174.6      66  198.88    65.5  277.59      66  378.51      66  412.53   66.69
   431.9      66  522.64      66  530.54   66.34   546.5   66.27  574.38    66.5
  582.74   65.99  587.92   65.84  612.66   65.69  621.15    65.5  630.92    64.5
  637.71   63.56  640.84   63.31  643.73   63.43  646.92   63.74  655.91      65
  662.28      65  672.78   65.35  676.48    65.5  812.64    65.5  901.35      65
#Mann= 0 , 0 , 0
Bank Sta=612.66,672.78
XS Rating Curve= 0 ,0
Exp/Cntr=0.3,0.1

Type RM Length L Ch R = 1 ,1600    ,134.48,200,216.46
XS GIS Cut Line= 4
    1074410.7849    1572827.1995    1074407.7038    1573267.6814
     1074434.311    1573387.4131    1074381.1515    1573722.5513
#Sta/Elev= 30
       0    65.4   11.05      65   57.27   64.92   79.08    65.5   83.31      66
   98.66      66  109.99    65.5  137.43    65.5  148.67   65.89  159.11    65.5
  226.78    65.5  254.02   65.24  296.01    65.5  357.63    65.5  372.13    65.8
  421.45   65.74  458.03      66  468.11      66   478.4    64.5  486.58    62.5
  488.75    62.5  497.83      64   505.2      65  526.76    65.5  635.79    65.5
  649.99   65.73  669.07    65.5  806.39   65.49  861.06      65  902.47   64.86
#Mann= 0 , 0 , 0
Bank Sta=458.03,526.76
XS Rating Curve= 0 ,0
Exp/Cntr=0.3,0.1

Type RM Length L Ch R = 1 ,1400    ,66.77,200,200.75
XS GIS Cut Line= 5
    1074368.4515    1572827.1995    1074385.1202    1573206.6128
    1074357.9785    1573331.6301    1074224.0756    1573430.5995
    1074182.1844    1573680.2179
#Sta/Elev= 30
       0    64.5   88.97    64.5  120.09   64.79  161.81   64.64  189.73   64.79
   227.3   64.81  244.67      65  312.31      65  323.28   65.09  359.04      65
  374.04   65.36  379.78   65.37   467.7   65.25   481.6      65  539.22      65
  548.07      65  563.68   63.72  573.68    62.5  579.47   62.09  585.76    61.8
  595.77   61.75  606.47      62  609.26    62.5  618.19    64.5  624.74      65
  627.91      65  679.73      65  773.02    64.5  863.42   64.52  927.33   64.42
#Mann= 0 , 0 , 0
Bank Sta=539.22,627.91
XS Rating Curve= 0 ,0
Exp/Cntr=0.3,0.1

Type RM Length L Ch R = 1 ,1200    ,254.92,200,253.54
XS GIS Cut Line= 6
    1074332.4681    1572829.3162    1074358.6619    1573204.4961
    1074325.3532    1573296.4952    1074191.9693    1573271.0397
    1074139.3303     1573305.863    1074061.5342    1573644.2345
#Sta/Elev= 30
       0   64.21   34.97    64.5   55.95    64.5   65.98   64.78      81    64.5
  257.81    64.5  279.04   64.78  287.64      65  475.11      65  487.74    65.5
  492.68    65.5  510.83      65  607.92      65   614.8    64.5  622.81      63
  625.67   62.21  627.91   62.06  630.11   62.17  633.89   62.63  636.05   62.96
  641.27      64  644.66    64.5  649.32      65  660.11      65  721.23      65
  786.94    64.5  818.68    64.5  921.71   64.22  944.22      64 1020.04      64
#Mann= 0 , 0 , 0
Bank Sta=492.68,660.11
XS Rating Curve= 0 ,0
Exp/Cntr=0.3,0.1

Type RM Length L Ch R = 1 ,1000    ,294.09,199.95,86.36
XS GIS Cut Line= 6
    1074294.1034     1572816.087    1074341.2283    1573203.2294
    1074321.0168    1573239.0549    1074204.6368    1573182.7241
    1074134.8528    1573197.2763    1074002.0028     1573628.624
#Sta/Elev= 24
       0   64.08   67.22    64.5  263.62    64.5  303.38      65  367.67      65
  369.72   64.94  373.31      65  437.44      65  440.71      65  455.92    64.5
   459.7      64  462.65    63.5  465.46   63.31  473.18   63.34  477.84      64
  483.82    64.5  520.23    64.5  616.26    64.5  628.94   64.75   670.4      65
  748.23      65  937.24      64 1033.94   63.98 1090.67    63.6
#Mann= 0 , 0 , 0
Bank Sta=437.44,520.23
XS Rating Curve= 0 ,0
Exp/Cntr=0.3,0.1

Type RM Length L Ch R = 1 ,800.0468,171.38,200.05,152.94
XS GIS Cut Line= 6
    1074201.2345    1572793.3328    1074191.8097    1572971.5487
    1074200.7204    1573157.4253    1074111.5405    1573169.8356
    1074055.1842    1573252.6504    1073963.9027    1573614.0719
#Sta/Elev= 30
       0    64.5  193.71    64.5  204.47      65  210.37   65.44  212.23   65.41
  221.63   64.95  243.44   64.73  268.99   64.69  281.96    64.5   288.6      64
  293.57    63.5  293.96   63.26  294.89      63  298.62    62.5  299.76    62.5
  305.81      62  311.51      62  319.51    63.5  323.67      64  329.11    64.5
     339    64.5  404.95    64.5  494.96   64.77  543.24    64.5  561.83    64.5
  574.71   64.64  619.68   64.76  767.17      64  872.08   63.86  927.54   63.57
#Mann= 0 , 0 , 0
Bank Sta=243.44,339
XS Rating Curve= 0 ,0
Exp/Cntr=0.3,0.1

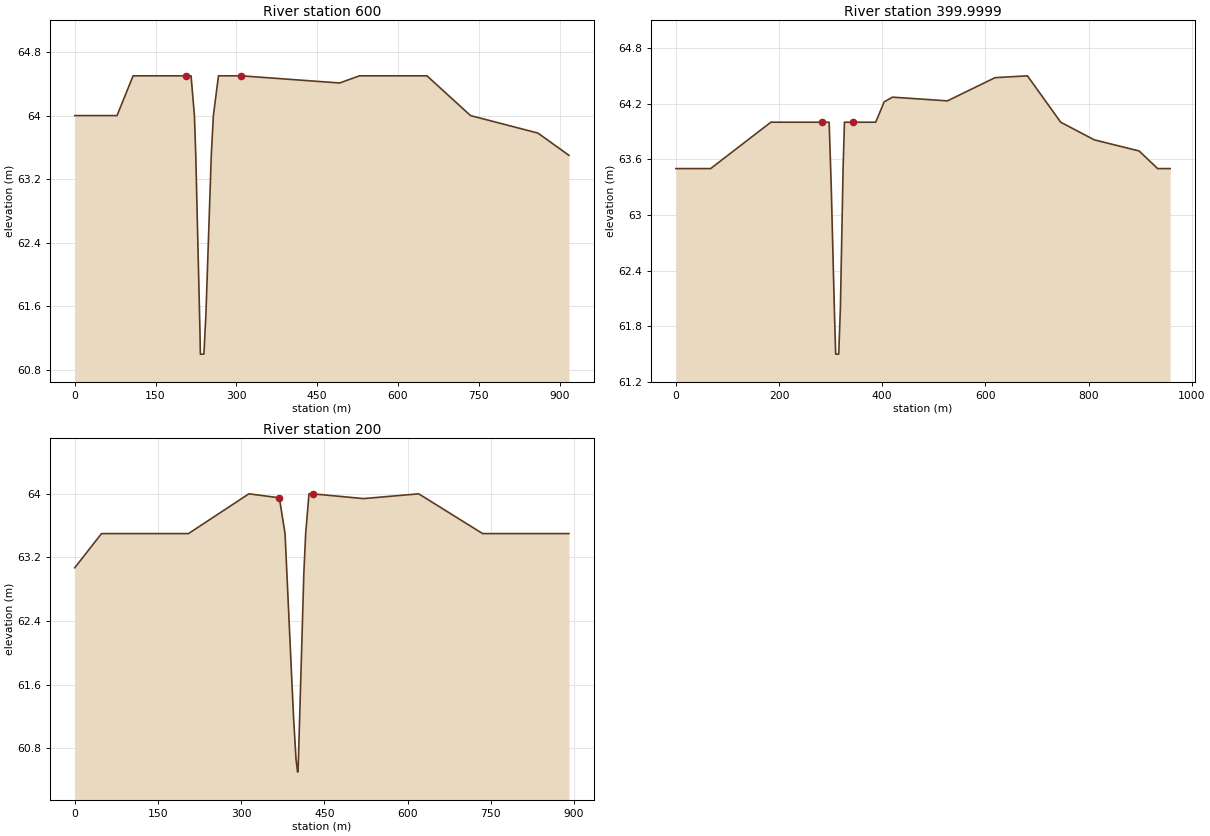
Type RM Length L Ch R = 1 ,600     ,201.9,200,218.01
XS GIS Cut Line= 5
    1074008.6174     1572759.466    1074030.2323    1572901.4454
    1074124.9951    1573025.8185    1074037.9862    1573171.6877
    1073937.4443    1573607.7219
#Sta/Elev= 21
       0      64   78.46      64  108.31    64.5  205.79    64.5  215.89    64.5
  222.13      64  224.65    63.5  232.46   61.27  233.18      61  239.72      61
  243.46    61.5  253.42    63.5   257.3      64  266.76    64.5  309.33    64.5
  491.73   64.41  528.45    64.5  653.76    64.5  734.64      64  859.78   63.78
   917.3    63.5
#Mann= 0 , 0 , 0
Bank Sta=205.79,309.33
XS Rating Curve= 0 ,0
Exp/Cntr=0.3,0.1

Type RM Length L Ch R = 1 ,399.9999,192.3,200,207.7
XS GIS Cut Line= 4
    1073767.3169     1572746.766    1073833.6822     1572915.828
    1074012.6483    1573073.2531    1073911.2505    1573601.9011
#Sta/Elev= 24
       0    63.5   67.28    63.5  184.11      64  283.39      64   297.1      64
  301.12   63.31  307.11      62  309.74    61.5  315.67    61.5  318.91      62
  324.11    63.5  326.74      64  343.39      64   387.3      64   403.9   64.22
  419.97   64.27  526.46   64.23  618.64   64.48  681.57    64.5  746.05      64
  811.16   63.81   898.1   63.69  934.08    63.5  958.26    63.5
#Mann= 0 , 0 , 0
Bank Sta=283.39,343.39
XS Rating Curve= 0 ,0
Exp/Cntr=0.3,0.1

Type RM Length L Ch R = 1 ,200     ,205.41,200,196.46
XS GIS Cut Line= 4
    1073640.3167    1572763.6994    1073700.5868    1573007.8409
    1073879.6812    1573275.1143    1073830.8171     1573589.201
#Sta/Elev= 19
       0   63.07   48.22    63.5  205.12    63.5     314      64  368.89   63.95
  379.18    63.5  394.34   61.21  398.95   60.66  401.86    60.5  402.68   60.54
  403.56   60.72  413.06      63  416.37    63.5  422.34      64  428.89      64
  520.84   63.94  620.22      64   735.4    63.5  891.07    63.5
#Mann= 0 , 0 , 0
Bank Sta=368.89,428.89
XS Rating Curve= 0 ,0
Exp/Cntr=0.3,0.1
LCMann Table=0

Chan Stop Cuts=-1
Use User Specified Reach Order=0
Composite Channel Slope=5